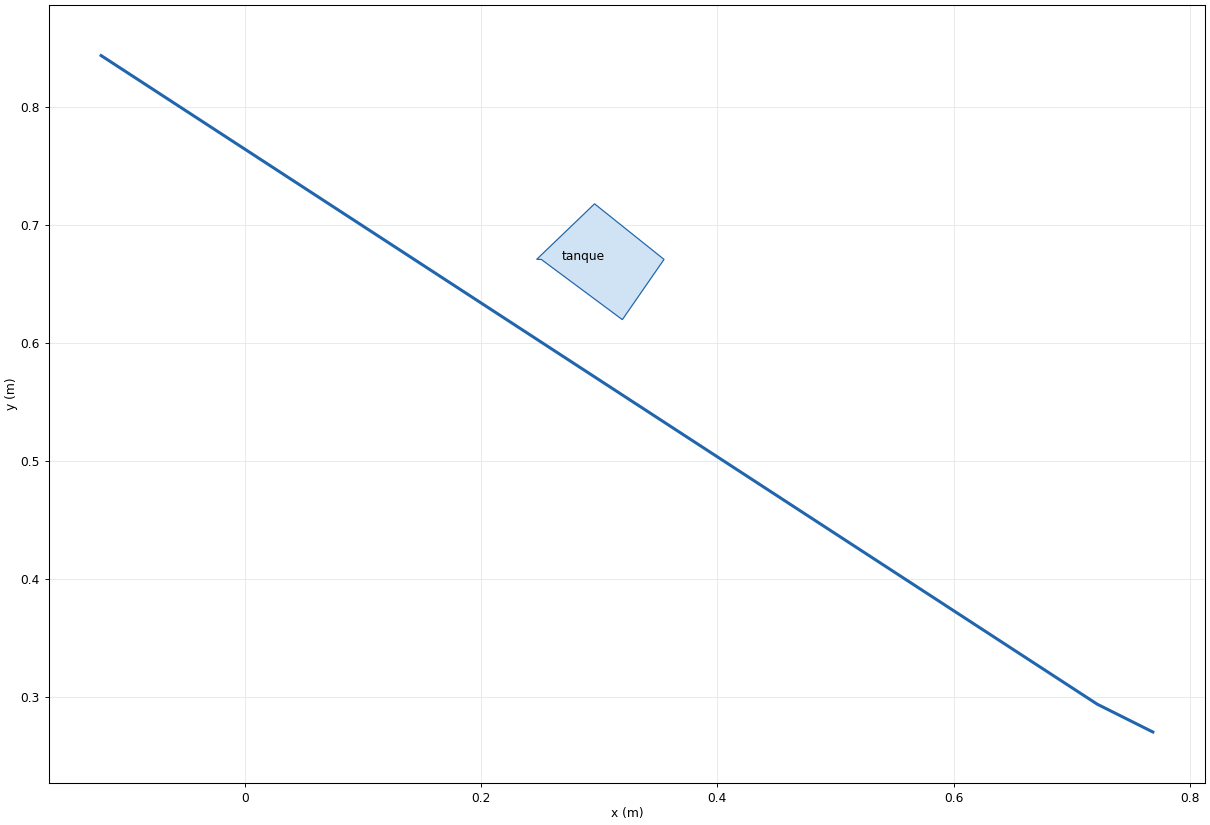
--- RCpumps.prj (project) ---

Proj Title=RCpumps
Current Plan=p01
Default Exp/Contr=0.3,0.1
SI Units
Geom File=g01
Unsteady File=u01
Plan File=p01
Y Axis Title=Elevation
X Axis Title(PF)=Main Channel Distance
X Axis Title(XS)=Station
BEGIN DESCRIPTION:
END DESCRIPTION:
DSS File=dss
DSS Export Rating Curves= 0
DSS Export Rating Curve Sorted= 0
DSS Export Volume Flow Curves= 0
DXF OffsetX= 0
DXF OffsetY= 0
DXF ScaleX= 1
DXF ScaleY= 10

--- RCpumps.p01 (plan) ---

Plan Title=Plan 01
Program Version=5.03
Short Identifier=Plan 01
Simulation Date=18OCT2017,0100,18OCT2017,2300
Geom File=g01
Flow File=u01
Subcritical Flow
K Sum by GR= 0
Std Step Tol= 0.003
Critical Tol= 0.003
Num of Std Step Trials= 20
Max Error Tol= 0.1
Flow Tol Ratio= 0.001
Split Flow NTrial= 30
Split Flow Tol= 0.006
Split Flow Ratio= 0.02
Log Output Level= 0
Friction Slope Method= 1
Unsteady Friction Slope Method= 2
Unsteady Bridges Friction Slope Method= 1
Parabolic Critical Depth
Global Vel Dist= 0 , 0 , 0
Global Log Level= 0
CheckData=Verdadero
Encroach Param=-1 ,0,0, 0
Computation Interval=10SEC
Output Interval=1HOUR
Instantaneous Interval=1HOUR
Mapping Interval=1HOUR
Run HTab= 1
Run UNet= 1
Run Sediment= 0
Run PostProcess= 1
Run WQNet= 0
Run RASMapper= 0
UNET Theta= 1
UNET Theta Warmup= 1
UNET ZTol= 0.006
UNET ZSATol= 0.006
UNET MxIter= 20
UNET Max Iter WO Improvement= 0
UNET MaxInSteps= 0
UNET DtIC= 0
UNET DtMin= 0
UNET MaxCRTS= 20
UNET WFStab= 2
UNET SFStab= 1
UNET WFX= 1
UNET SFX= 1
UNET DSS MLevel= 4
UNET Pardiso=0
UNET DZMax Abort= 30
UNET Use Existing IB Tables=-1
UNET Froude Reduction=Verdadero
UNET Froude Limit= 0.8
UNET Froude Power= 4
UNET Time Slicing=0,0, 5
UNET D1 Cores= 0
UNET D2 Coriolis=0
UNET D2 Cores= 0
UNET D2 Theta= 1
UNET D2 Theta Warmup= 1
UNET D2 Z Tol= 0.003
UNET D2 Volume Tol= 0.003
UNET D2 Max Iterations= 20
UNET D2 Equation= 0
UNET D2 RampUpFraction=0.1
UNET D2 TimeSlices= 1
UNET D2 BCVolumeCheck=0
UNET D1D2 MaxIter= 0
UNET D1D2 ZTol=0.003
UNET D1D2 QTol=0.1
UNET D1D2 MinQTol=0.03
DSS File=dss
Write IC File= 0
Write IC File at Fixed DateTime=0
Write IC File at Sim End=0
Echo Input=Falso
Echo Parameters=Falso
Echo Output=Falso
Write Detailed= 0
HDF Write Warmup=0
HDF Write Time Slices=0
HDF Flush=0
HDF Face Node Velocities=0
HDF Compression= 1
HDF Chunk Size= 1
HDF Spatial Parts= 1
HDF Use Max Rows=0
HDF Fixed Rows= 1
Calibration Method= 0
Calibration Iterations= 20
Calibration Max Change=0.05
Calibration Tolerance=0.2
Calibration Maximum=1.5
Calibration Minimum=0.5
Calibration Optimization Method= 1
WQ AD Non Conservative
WQ ULTIMATE=-1
WQ Max Comp Step=1HOUR
WQ Output Interval=15MIN
WQ Output Selected Increments= 0
WQ Output face flow=0
WQ Output face velocity=0
WQ Output face area=0
WQ Output face dispersion=0
WQ Output cell volume=0
WQ Output cell surface area=0
WQ Output cell continuity=0
WQ Output cumulative cell continuity=0
WQ Output face conc=0
WQ Output face dconc_dx=0
WQ Output face courant=0
WQ Output face peclet=0
WQ Output face adv mass=0
WQ Output face disp mass=0
WQ Output cell mass=0
WQ Output cell source sink temp=0
WQ Output nsm pathways=0
WQ Output nsm derived pathways=0
WQ Output MaxMinRange=-1
WQ Daily Max Min Mean=-1
WQ Daily Range=0
WQ Daily Time=0
WQ Create Restart=0
WQ Fixed Restart=0
WQ System Summary=0
WQ Write To DSS=0
WQ Use Fixed Temperature=0
Sorting and Armoring Iterations= 10
XS Update Threshold= 0.02
Bed Roughness Predictor= 0
Hydraulics Update Threshold= 0.02
Energy Slope Method= 1
Volume Change Method= 1
Sediment Retention Method= 0
XS Weighting Method= 0
Number of US Weighted Cross Sections= 1
Number of DS Weighted Cross Sections= 1
Upstream XS Weight=0
Main XS Weight=1
Downstream XS Weight=0
Number of DS XS's Weighted with US Boundary= 1
Upstream Boundary Weight= 1
Weight of XSs Associated with US Boundary= 0
Number of US XS's Weighted with DS Boundary= 1
Downstream Boundary Weight= 0.5
Weight of XSs Associated with DS Boundary= 0.5
Percentile Method= 0
Sediment Output Level= 4
Mass or Volume Output= 0
Output Increment Type= 1
Profile and TS Output Increment= 1
XS Output Flag= 0
XS Output Increment= 10
Write Gradation File= 0
Read Gradation Hotstart= 0
Write HDF5 File= 1
Write DSS Sediment File= 0
SV Curve= 0
Specific Gage Flag= 0

--- RCpumps.u01 (unsteady flow) ---

Flow Title=Unsteady
Program Version=5.03
Use Restart= 0
Initial Flow Loc=canal           ,uno             ,1000    ,10
Boundary Location=canal           ,uno             ,1000    ,        ,                ,                ,                ,
Interval=1HOUR
Flow Hydrograph= 100
       0     2.5       5     7.5      10    12.5      15    17.5      20    22.5
      25    27.5      30   28.97   27.93    26.9   25.86   24.83   23.79   22.76
   21.72   20.69   19.66   18.62   17.59   16.55   15.52   14.48   13.45   12.41
   11.38   10.34    9.31    8.28    7.24    6.21    5.17    4.14     3.1    2.07
    1.03       0       0       0       0       0       0       0       0       0
       0       0       0       0       0       0       0       0       0       0
       0       0       0       0       0       0       0       0       0       0
       0       0       0       0       0       0       0       0       0       0
       0       0       0       0       0       0       0       0       0       0
       0       0       0       0       0       0       0       0       0       0
Use DSS=Falso
Use Fixed Start Time=Verdadero
Fixed Start Date/Time=18OCT2017,0100
Is Critical Boundary=Falso
Boundary Location=canal           ,uno             ,0       ,        ,                ,                ,                ,
Friction Slope=0.001

--- RCpumps.g01 (geometry) ---

Geom Title=geo
Program Version=5.03

River Reach=canal           ,uno
Reach XY= 3
-0.12156862745090.843137254901960.721568627450980.29411764705882
0.768627450980390.27058823529412

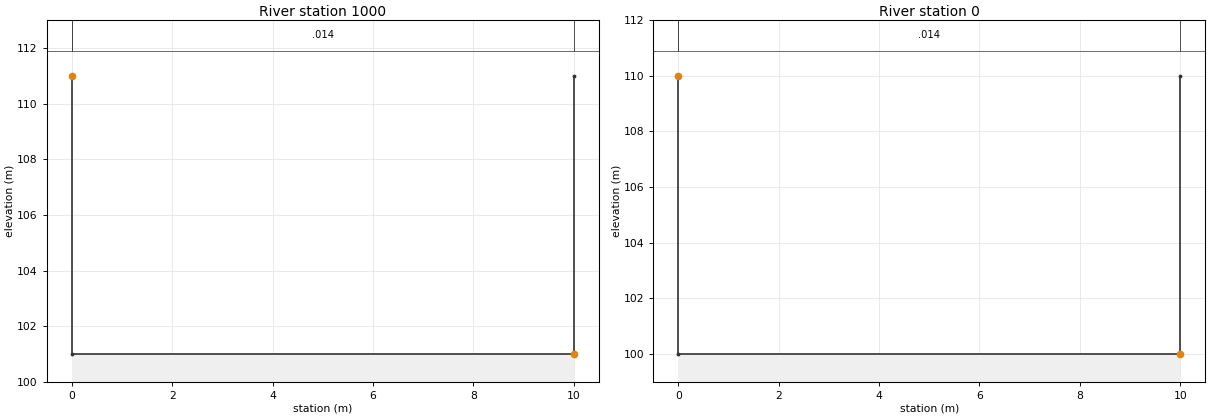
Type RM Length L Ch R = 1 ,1000    ,50,50,50
#Sta/Elev= 4
       0     111       0     101      10     101      10     111
#Mann= 3 , 0 , 0
       0    .014       0       0    .014       0      10    .014       0
Bank Sta=0,10
XS Rating Curve= 0 ,0
Exp/Cntr=0.3,0.1

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
Type RM Length L Ch R = 1 ,0       ,0,0,0
#Sta/Elev= 4
       0     110       0     100      10     100      10     110
#Mann= 3 , 0 , 0
       0    .014       0       0    .014       0      10    .014       0
Bank Sta=0,10
XS Rating Curve= 0 ,0
Exp/Cntr=0.3,0.1

Storage Area=tanque          ,0.3028541,0.6692704
Storage Area Surface Line= 6
0.250980392156860.67058823529412
0.319607843137260.61960784313726
0.354901960784310.67058823529412
0.296078431372550.71764705882353
0.247058823529410.67058823529412
0.250980392156860.67058823529412
Storage Area Type= 0
Storage Area Area=10000
Storage Area Min Elev=105
Storage Area Vol Elev= 1
               0
Storage Area Is2D=0
Storage Area Point Generation Data=0,0,,
Storage Area 2D Points= 0
Storage Area Mannings=0.06
2D Cell Volume Filter Tolerance=0.003
2D Face Profile Filter Tolerance=0.003
2D Face Area Elevation Profile Filter Tolerance=0.003
2D Face Area Elevation Conveyance Ratio=0.02

Pump Station=B1              ,0.2242877,0.7122779,,,0.2242877,0.7122779
Pump Station From=canal           ,uno             ,650.00* ,                ,0
Pump Station To=                ,                ,        ,tanque          ,
Pump Station TW Min=112
Pump Station Group=Group #1        ,Falso,0,0
Pump Station Group Pump=Pump #1         ,106,110
Pump Station Group HQ= 2
       0       2      10       2
LCMann Table=0

Chan Stop Cuts=-1
Use User Specified Reach Order=0
Composite Channel Slope=5